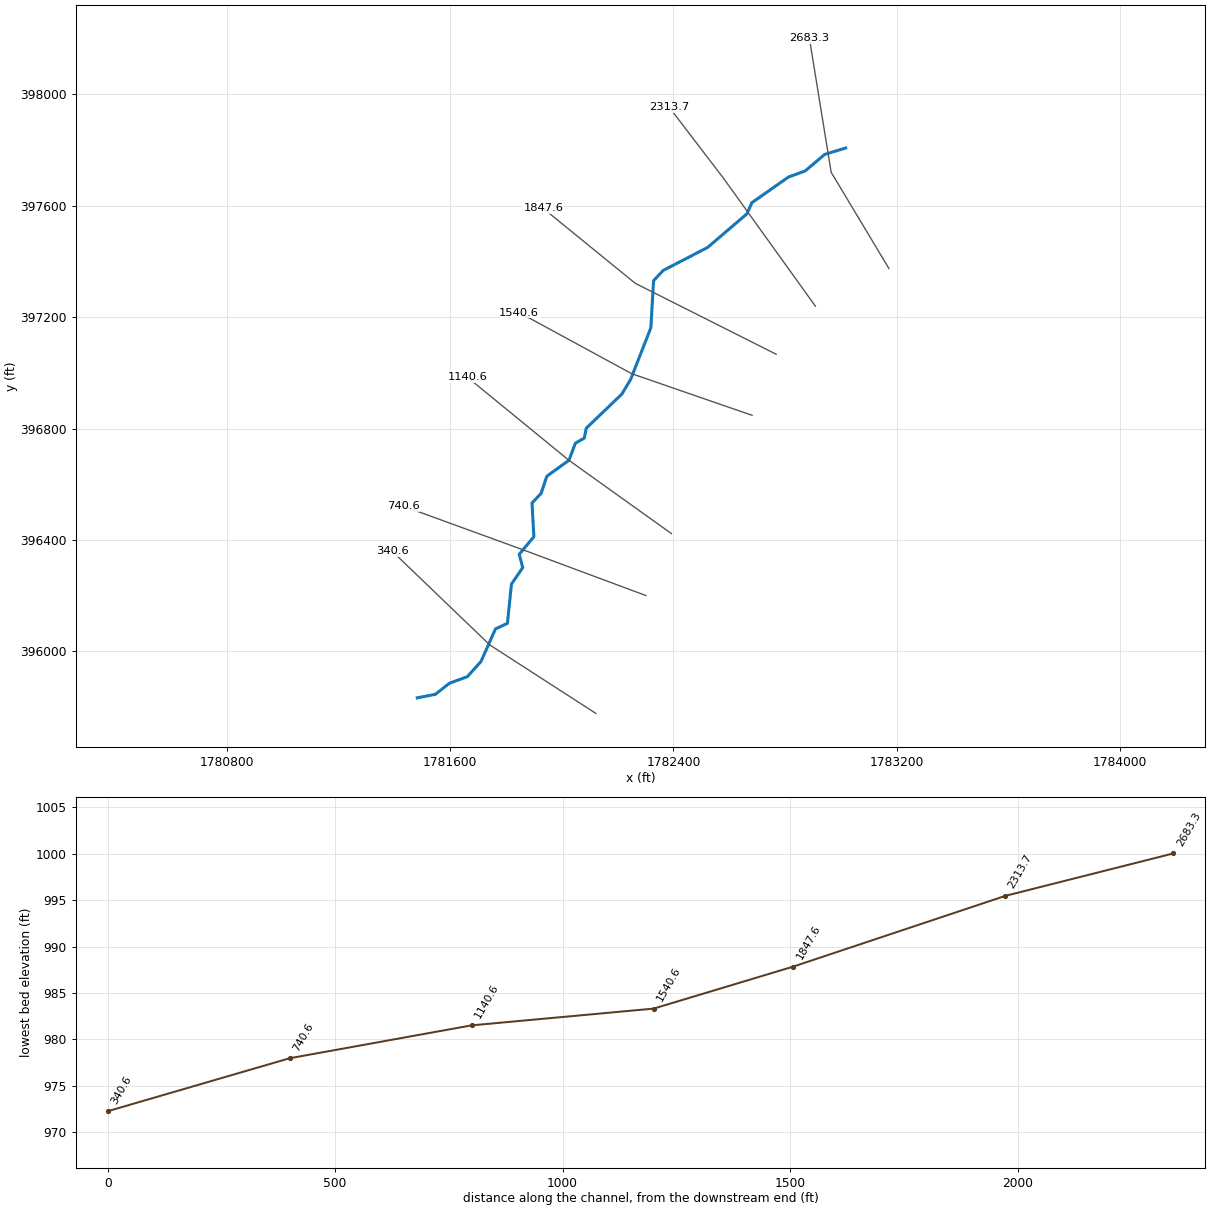
--- ChckRn.prj (project) ---

Proj Title=ChckRn
Current Plan=p01
Default Exp/Contr=0,0
English Units
Geom File=g01
Flow File=f01
Plan File=p01
BEGIN DESCRIPTION:
END DESCRIPTION:
DSS Export Rating Curves= 0
DSS Export Rating Curve Sorted= 0
DSS Export Volume Flow Curves= 0
DXF OffsetX= 0
DXF OffsetY= 0
DXF ScaleX= 0
DXF ScaleY= 0

--- ChckRn.p01 (plan) ---

Plan Title=Floodplain
Program Version=4.00
Geom File=g01
Flow File=f01
K Sum by GR=0
Std Step Tol=0.01
Critical Tol=0.01
Num of Std Step Trials=20
Max Error Tol=0.3
Flow Tol Ratio=0.001
Split Flow NTrial=30
Split Flow Tol=0.02
Split Flow Ratio=0.02
Log Output Level=0
Friction Slope Method=1
Unsteady Friction Slope Method=2
Unsteady Bridges Friction Slope Method=1
Global Log Level=0
CheckData=False
Run HTab=0
Run UNet=0
Run PostProcess=0
UNET Theta=0
UNET Theta Warmup=0
UNET ZTol=0
UNET ZSATol=0
UNET MxIter=0
UNET MaxInSteps=0
UNET DtIC=0
UNET DtMin=0
UNET MaxCRTS=0
UNET WFStab=0
UNET SFStab=0
UNET WFX=0
UNET SFX=0
UNET DSS MLevel=0
UNET DZMax Abort=0
UNET Convert EG Bridges=0
UNET Use Existing IB Tables=0
UNET Froude Limit=0
UNET Froude Power=0
Write IC File=0
Echo Input=False
Echo Output=False
Write Detailed=0

--- ChckRn.f01 (steady flow) ---

Flow Title=NFF Regression Equation
Program Version=4.00
Number of Profiles=1
Profile Names=P100yr
River Rch & RM=ChckRn,Main      ,2683.3
598.8954
River Rch & RM=ChckRn,Main      ,1847.6
618.1768
River Rch & RM=ChckRn,Main      ,1540.6
828.2421
River Rch & RM=ChckRn,Main      ,340.6
847.6105
Boundary for River Rch & Prof#=ChckRn,Main      ,1
Up Type=0
Dn Type=3
Dn Slope=0.012369

--- ChckRn.g01 (geometry) ---

Geom Title=USGS 3m DEM
Program Version=4.00

River Reach=ChckRn     ,Main
Reach XY= 30
     1783017.073      397807.678     1782942.402      397784.839
     1782871.854      397725.088     1782812.309      397703.420
     1782681.287      397611.384     1782663.608      397571.396
     1782522.498      397450.553     1782363.339      397368.007
     1782328.768      397331.074     1782319.068      397162.126
     1782247.128      396977.759     1782215.409      396924.136
     1782087.556      396801.305     1782080.538      396765.757
     1782048.465      396747.492     1782025.666      396686.170
     1781946.249      396628.930     1781925.954      396567.590
     1781893.143      396532.599     1781899.667      396411.282
     1781847.280      396348.530     1781859.684      396300.749
     1781819.271      396240.779     1781804.959      396100.320
     1781762.149      396080.485     1781710.211      395963.385
     1781660.999      395908.487     1781596.758      395885.025
     1781546.855      395845.398     1781481.654      395832.629

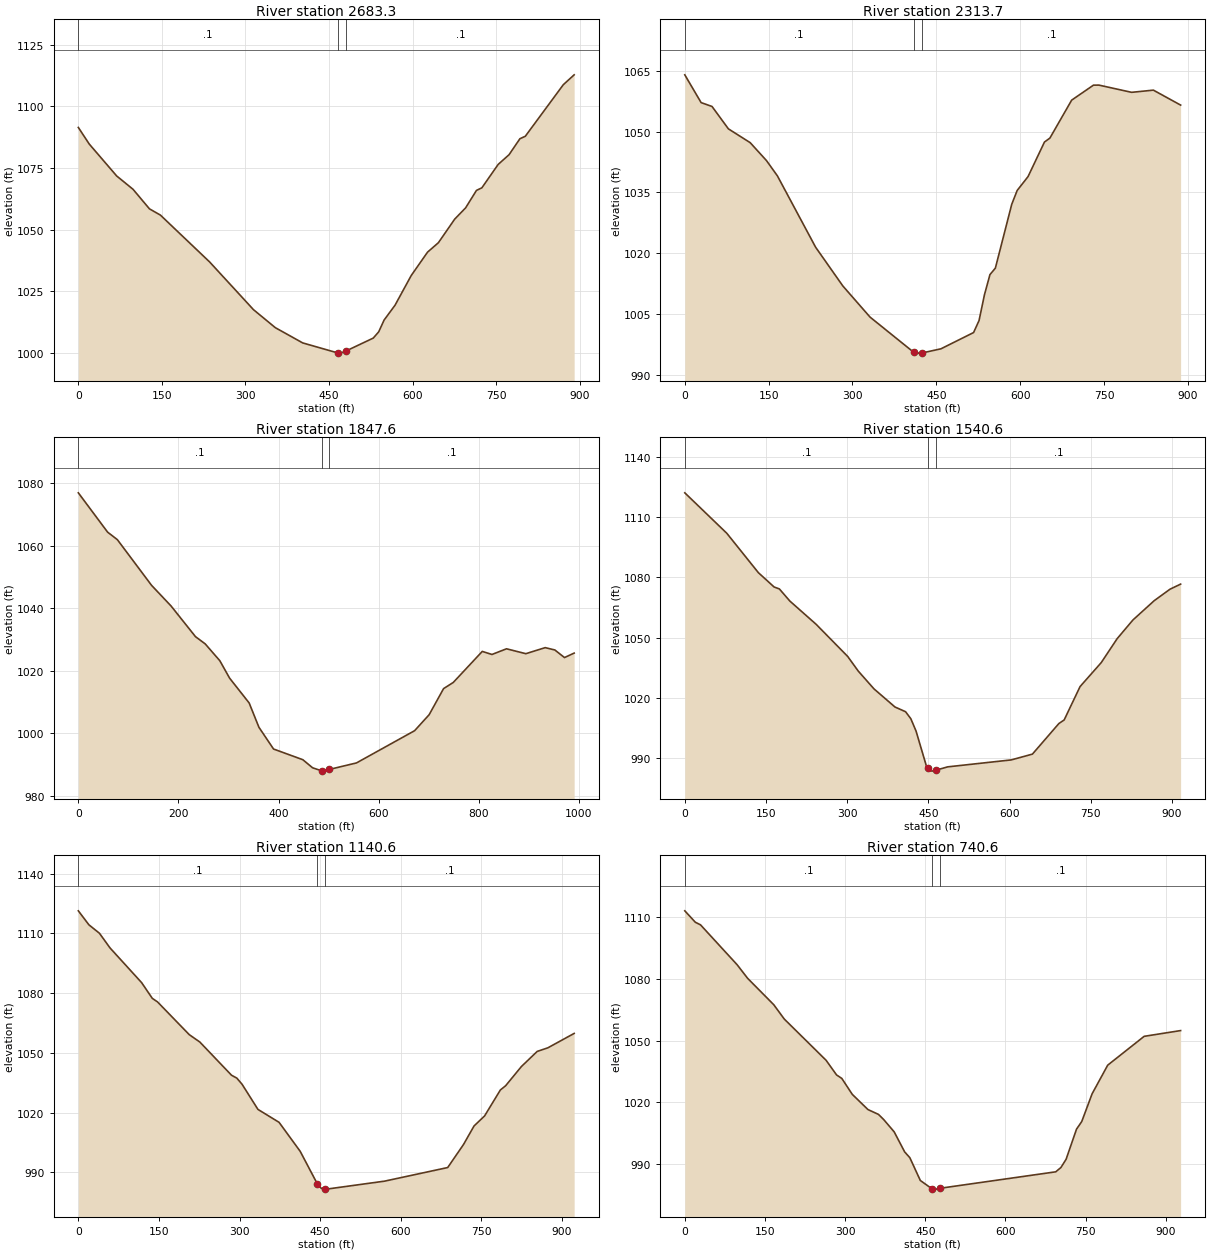
Type RM Length L Ch R = 1 ,2683.3,360.235,369.684,378.099
XS GIS Cut Line= 3
     1783172.305      397374.919     1782965.368      397720.501
     1782887.342      398201.658
#Sta/Elev= 30
       0 1091.45    19.6 1084.72    68.8 1071.80    98.2 1066.39   127.7 1058.47
   147.4 1055.93   235.8 1036.94   314.4 1017.64   353.7 1010.33   402.8 1004.16
   466.3 1000.06   471.0 1000.02   481.3 1000.96   529.5 1006.11   539.3 1008.65
   549.0 1013.43   568.5 1019.39   597.8 1031.50   627.0 1040.93   646.5 1044.76
   675.8 1054.32   695.3 1058.86   714.8 1065.94   724.5 1066.99   753.8 1076.47
   773.3 1080.39   792.8 1086.87   802.5 1087.87   870.7 1108.75   890.2 1112.76
#Mann= 3 , 0 , 0
       0     0.1       0   466.3   0.045       0   481.3     0.1       0
Bank Sta=   466.3,   481.3
Exp/Cntr=0.3,0.1

Type RM Length L Ch R = 1 ,2313.7,459.026,466.096,478.248
XS GIS Cut Line= 3
     1782909.016      397239.344     1782579.575      397698.827
     1782384.511      397954.577
#Sta/Elev= 30
       0 1063.96    29.2 1057.12    48.7 1056.17    78.0 1050.66   117.0 1047.26
   146.2 1042.84   165.7 1039.08   234.0 1021.53   282.7 1011.99   331.4 1004.32
   409.4  995.67   419.2  995.45   424.4  995.49   458.2  996.51   516.6 1000.51
   526.4 1003.47   536.1 1009.83   545.9 1014.78   555.6 1016.38   584.9 1032.10
   594.6 1035.49   614.1 1038.92   643.4 1047.41   653.1 1048.38   692.1 1057.73
   731.1 1061.42   740.8 1061.43   799.3 1059.65   838.3 1060.19   887.0 1056.51
#Mann= 3 , 0 , 0
       0     0.1       0   409.4   0.045       0   424.4     0.1       0
Bank Sta=   409.4,   424.4
Exp/Cntr=0.3,0.1

Type RM Length L Ch R = 1 ,1847.6,302.447,306.931,307.685
XS GIS Cut Line= 3
     1782768.213      397066.968     1782263.138      397321.704
     1781933.697      397590.458
#Sta/Elev= 30
       0 1076.97    58.5 1064.38    78.0 1061.97   146.3 1047.35   185.3 1040.73
   234.1 1030.91   253.6 1028.58   282.8 1023.19   302.3 1017.62   341.4 1009.66
   360.9 1001.88   390.1  994.92   448.6  991.50   468.1  988.91   486.2  987.94
   487.7  987.84   501.2  988.37   555.9  990.47   672.0 1000.79   701.0 1005.90
   729.9 1014.27   749.3 1016.25   807.2 1026.18   826.6 1025.20   855.6 1027.02
   894.2 1025.45   932.9 1027.39   952.2 1026.64   971.5 1024.21   990.8 1025.64
#Mann= 3 , 0 , 0
       0     0.1       0   486.2   0.045       0   501.2     0.1       0
Bank Sta=   486.2,   501.2
Exp/Cntr=0.3,0.1

Type RM Length L Ch R = 1 ,1540.6,406.316,400,396.208
XS GIS Cut Line= 3
     1782681.955      396847.596     1782250.879      396996.840
     1781847.281      397216.641
#Sta/Elev= 30
       0 1122.26    77.6 1102.06   135.9 1082.40   165.0 1075.24   174.7 1074.27
   194.1 1068.21   242.6 1056.61   300.9 1040.56   320.3 1033.28   349.4 1024.38
   388.2 1015.33   407.7 1012.99   417.4 1009.50   427.1 1003.32   446.5  985.57
   448.7  985.06   456.2  983.32   463.7  983.78   485.5  985.45   602.9  988.92
   642.0  991.81   690.9 1007.09   700.6 1008.86   730.0 1025.53   769.1 1037.50
   798.4 1049.42   827.7 1058.80   866.9 1068.41   896.2 1074.16   915.7 1076.68
#Mann= 3 , 0 , 0
       0     0.1       0   448.7   0.045       0   463.7     0.1       0
Bank Sta=   448.7,   463.7
Exp/Cntr=0.3,0.1

Type RM Length L Ch R = 1 ,1140.6,392.564,400,407.684
XS GIS Cut Line= 3
     1782392.870      396422.672     1782025.366      396686.022
     1781661.533      396984.234
#Sta/Elev= 30
       0 1121.28    19.7 1114.25    39.3 1110.01    59.0 1102.64   117.9 1085.18
   137.6 1077.33   147.4 1075.53   206.4 1059.10   226.1 1055.39   285.0 1038.73
   294.9 1037.27   304.7 1034.18   334.2 1021.56   373.5 1015.07   412.8 1000.52
   444.6  984.22   452.1  981.91   459.6  981.61   461.9  981.52   569.7  985.52
   687.3  992.36   716.7 1003.92   736.3 1013.23   755.9 1018.27   785.3 1031.31
   795.1 1033.44   824.5 1043.10   853.9 1050.69   873.5 1052.46   922.6 1059.71
#Mann= 3 , 0 , 0
       0     0.1       0   444.6   0.045       0   459.6     0.1       0
Bank Sta=   444.6,   459.6
Exp/Cntr=0.3,0.1

Type RM Length L Ch R = 1 ,740.6,405.926,400,389.135
XS GIS Cut Line= 3
     1782300.820      396200.338     1781860.362      396364.674
     1781430.472      396521.633
#Sta/Elev= 30
       0 1112.89    19.6 1107.38    29.4 1106.10    97.9 1086.77   117.5 1080.19
   166.5 1067.37   186.1 1060.44   264.4 1040.44   284.0 1033.33   293.8 1031.65
   313.4 1023.92   342.8 1016.54   362.4 1014.21   372.2 1011.70   391.8 1005.75
   411.4  996.03   421.1  993.23   440.7  982.18   462.6  978.13   470.1  977.98
   477.6  978.39   694.1  986.37   703.8  988.45   713.5  992.45   733.0 1007.05
   742.8 1010.76   762.2 1024.21   791.4 1038.08   859.6 1052.05   927.8 1054.84
#Mann= 3 , 0 , 0
       0     0.1       0   462.6   0.045       0   477.6     0.1       0
Bank Sta=   462.6,   477.6
Exp/Cntr=0.3,0.1

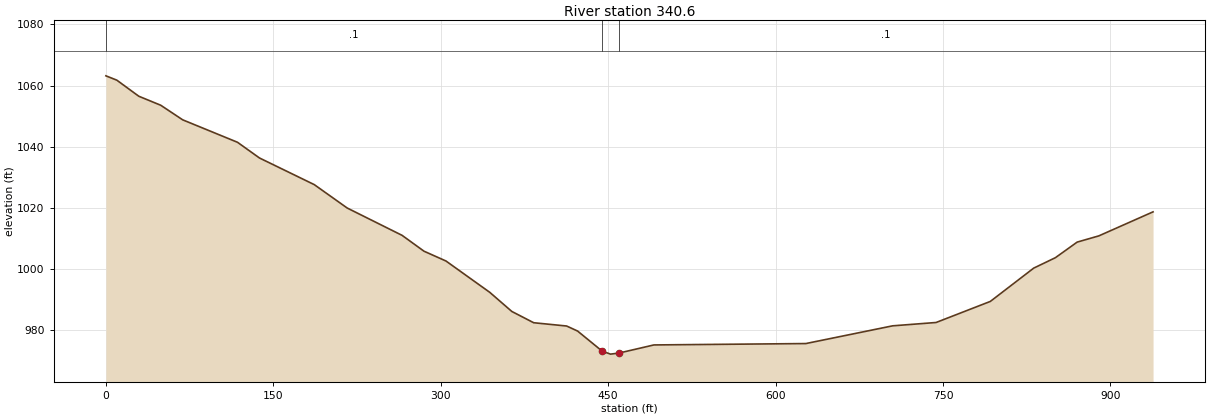
Type RM Length L Ch R = 1 ,340.6,359.042,340.638,327.191
XS GIS Cut Line= 3
     1782121.875      395776.937     1781742.182      396022.397
     1781391.854      396359.389
#Sta/Elev= 30
       0 1063.16     9.8 1061.74    29.5 1056.49    49.1 1053.56    68.8 1048.79
   117.9 1041.46   137.6 1036.33   186.7 1027.63   216.2 1019.99   265.4 1011.06
   285.0 1005.89   304.7 1002.69   344.0  992.44   363.7  986.21   383.3  982.53
   412.8  981.46   422.6  979.82   444.6  973.27   452.1  972.28   459.6  972.62
   491.0  975.28   627.1  975.73   704.9  981.52   743.8  982.61   792.4  989.49
   831.3 1000.37   850.7 1003.77   870.2 1008.86   889.6 1010.89   938.2 1018.74
#Mann= 3 , 0 , 0
       0     0.1       0   444.6   0.045       0   459.6     0.1       0
Bank Sta=   444.6,   459.6
Exp/Cntr=0.3,0.1